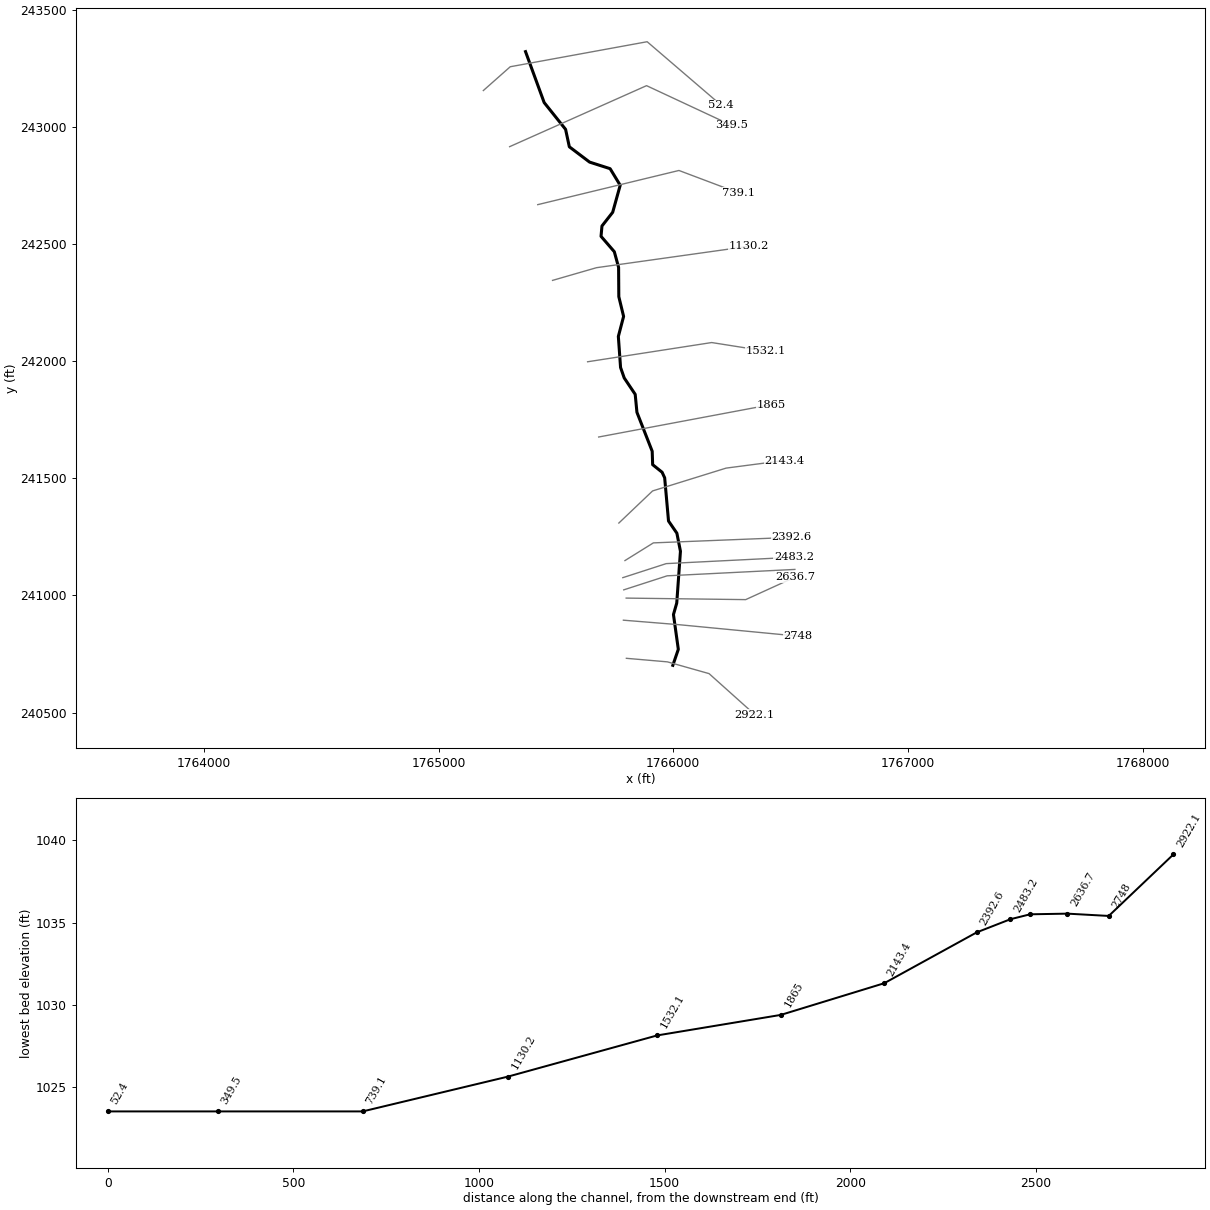
--- ARNOLDRN.prj (project) ---

Proj Title=ARNOLDRN
Current Plan=p01
Default Exp/Contr=0,0
English Units
Geom File=g01
Flow File=f01
Plan File=p01
BEGIN DESCRIPTION:
END DESCRIPTION:
DSS Export Rating Curves= 0
DSS Export Rating Curve Sorted= 0
DSS Export Volume Flow Curves= 0
DXF OffsetX= 0
DXF OffsetY= 0
DXF ScaleX= 0
DXF ScaleY= 0

--- ARNOLDRN.p01 (plan) ---

Plan Title=Floodplain
Program Version=4.00
Geom File=g01
Flow File=f01
K Sum by GR=0
Std Step Tol=0.01
Critical Tol=0.01
Num of Std Step Trials=20
Max Error Tol=0.3
Flow Tol Ratio=0.001
Split Flow NTrial=30
Split Flow Tol=0.02
Split Flow Ratio=0.02
Log Output Level=0
Friction Slope Method=1
Unsteady Friction Slope Method=2
Unsteady Bridges Friction Slope Method=1
Global Log Level=0
CheckData=False
Run HTab=0
Run UNet=0
Run PostProcess=0
UNET Theta=0
UNET Theta Warmup=0
UNET ZTol=0
UNET ZSATol=0
UNET MxIter=0
UNET MaxInSteps=0
UNET DtIC=0
UNET DtMin=0
UNET MaxCRTS=0
UNET WFStab=0
UNET SFStab=0
UNET WFX=0
UNET SFX=0
UNET DSS MLevel=0
UNET DZMax Abort=0
UNET Convert EG Bridges=0
UNET Use Existing IB Tables=0
UNET Froude Limit=0
UNET Froude Power=0
Write IC File=0
Echo Input=False
Echo Output=False
Write Detailed=0

--- ARNOLDRN.f01 (steady flow) ---

Flow Title=NFF Regression Equation
Program Version=4.10
Number of Profiles= 1
Profile Names=P100yr
River Rch & RM=ARNOLDRN,Main            ,2922.1
788.0956
River Rch & RM=ARNOLDRN,Main            ,2636.7
789.6502
River Rch & RM=ARNOLDRN,Main            ,2392.6
996.9709
River Rch & RM=ARNOLDRN,Main            ,349.5
1041.868
River Rch & RM=ARNOLDRN,Main            ,52.4
1045.803
Boundary for River Rch & Prof#=ARNOLDRN,Main            , 1
Up Type= 0
Dn Type= 3
Dn Slope=0.00549
DSS Import GetInterval= 0
DSS Import GetPeak= 0
DSS Import FillOption= 0

--- ARNOLDRN.g01 (geometry) ---

Geom Title=USGS 10m DEM
Program Version=4.10

River Reach=ARNOLDRN        ,Main
Reach XY= 30
       1765998.1      240701.484     1766021.403      240769.768
     1766000.713      240918.143     1766014.724      240967.325
     1766030.484      241188.172     1766015.295      241265.289
      1765979.67      241317.322     1765963.269      241501.675
      1765952.26       241525.55     1765912.096      241557.812
     1765910.121      241615.094     1765845.127      241781.188
     1765837.695      241858.051     1765790.948      241927.843
     1765775.373      241972.572     1765765.928      242104.957
     1765788.314      242190.552     1765767.903      242274.829
     1765766.993      242399.765     1765748.764      242466.605
     1765692.185       242532.27     1765696.135      242576.385
     1765741.824      242634.891     1765773.829      242750.207
     1765730.916      242821.009     1765643.461      242849.067
     1765557.141      242914.409     1765541.147      242988.838
      1765449.88      243103.203     1765370.508      243320.576

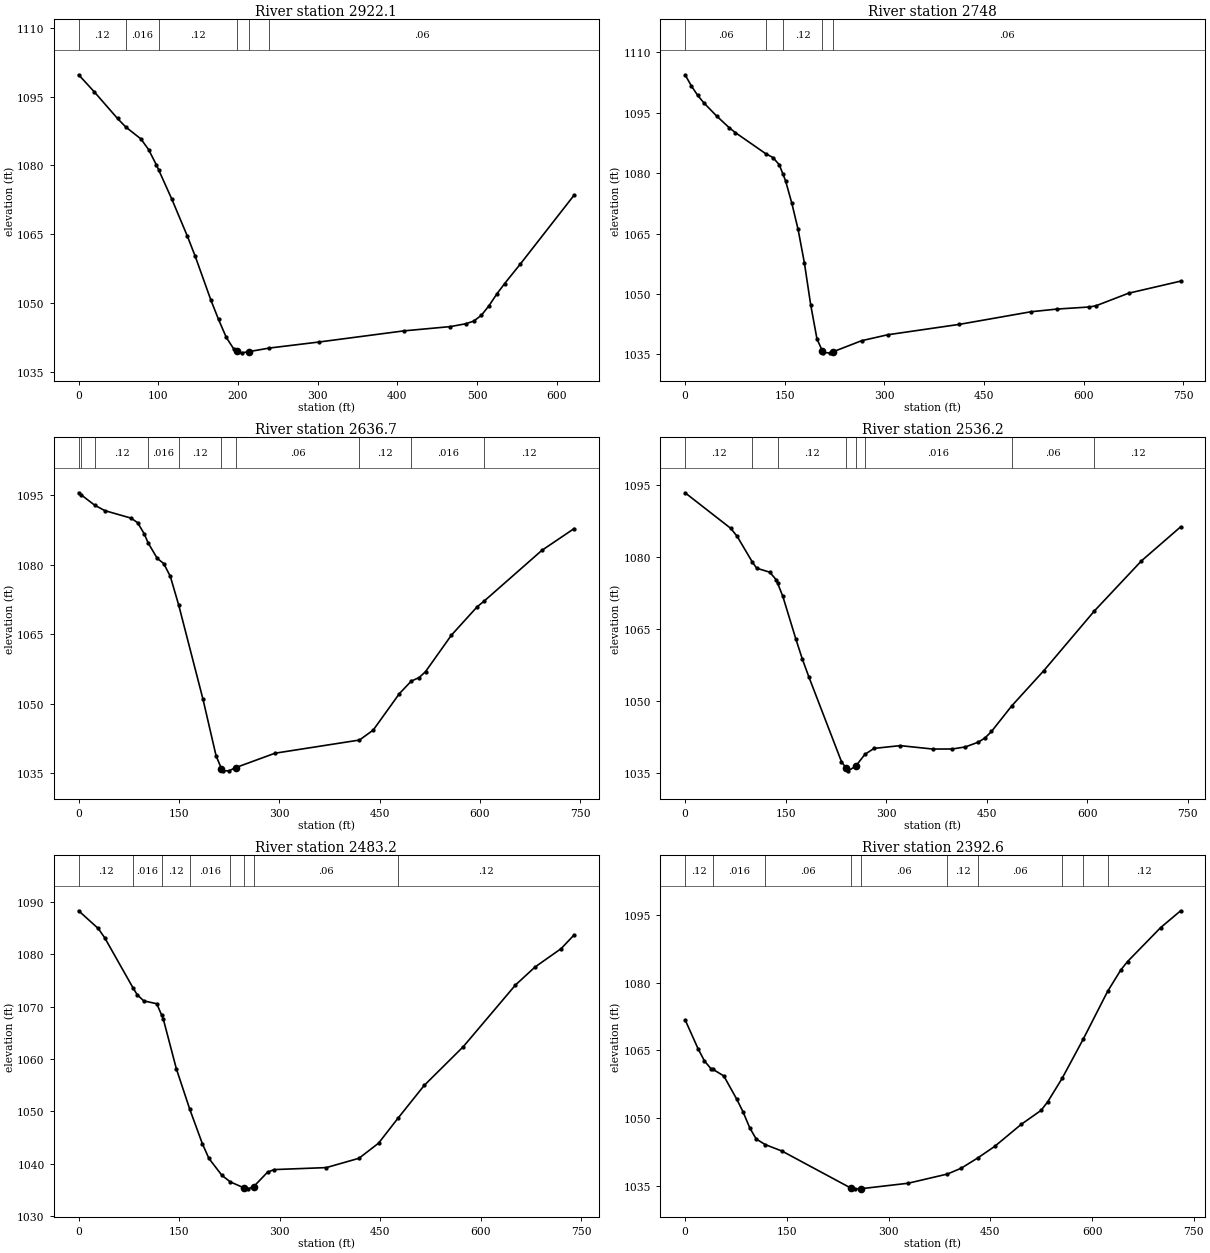
Type RM Length L Ch R = 1 ,2922.1  ,169.3,174.2,178.3
XS GIS Cut Line= 4
     1765800.119      240731.383     1765975.099      240716.207
     1766152.361      240666.059     1766347.495      240490.946
#Sta/Elev= 30
       0 1099.74    19.5 1096.05    48.8 1090.22   59.211088.356    78.1 1085.77
    87.8 1083.45    97.6  1080.1  100.44 1079.02   117.1 1072.59   136.6 1064.53
   146.4 1060.16   165.9 1050.69   175.6 1046.43   185.3 1042.53     195 1039.91
  198.84 1039.56   204.7 1039.15   214.4 1039.43   239.21040.188   301.7 1041.51
   408.4 1043.94   466.7 1044.87   486.1 1045.49   495.8 1046.06   505.5 1047.32
   515.2 1049.45   524.9 1051.97   534.6 1054.22   554.1 1058.43     622 1073.53
#Mann= 6 ,-1 , 0
       0     .12       0   59.21    .016       0  100.44     .12       0
  198.84    .045       0   214.4     .12       0   239.2     .06       0
Bank Sta=198.84,214.4
XS Rating Curve= 0 ,0
Exp/Cntr=0.3,0.1

Type RM Length L Ch R = 1 ,2748    ,109.7,111.3,112.6
XS GIS Cut Line= 3
     1765787.427      240894.076     1766022.947      240874.958
      1766530.19       240826.15
#Sta/Elev= 30
       0 1104.38     9.4 1101.63    18.9 1099.28    28.4 1097.38    47.3 1094.18
    66.2 1091.28    75.6 1090.04   121.41084.802   132.3 1083.85   141.8 1082.04
  147.241079.754   151.2 1078.09   160.7 1072.48   170.1    1066   179.6 1057.68
     189 1047.36   198.5 1038.85  206.62 1035.87   207.9 1035.44   217.4  1035.4
     223 1035.68   265.7 1038.41   304.9 1039.88   412.7 1042.46   520.5 1045.59
   559.7 1046.26   608.7 1046.78   618.5 1047.08   667.5 1050.19   745.9 1053.19
#Mann= 5 ,-1 , 0
       0     .06       0   121.4    .016       0  147.24     .12       0
  206.62    .045       0     223     .06       0
Bank Sta=206.62,223
XS Rating Curve= 0 ,0
Exp/Cntr=0.3,0.1

Type RM Length L Ch R = 1 ,2636.7  ,99.2,100.5,102
XS GIS Cut Line= 3
     1765799.317      240988.342     1766308.432      240981.832
      1766519.37      241078.186
#Sta/Elev= 30
       0 1095.47    3.24 1095.08   24.091092.789    39.2 1091.62    78.3 1090.01
    88.1 1089.04    97.9 1086.68  103.981084.657   117.5 1081.35   127.3 1080.21
   137.1 1077.46  149.61 1071.29     186 1050.96   205.6 1038.75  213.63 1036.01
   215.4 1035.56   224.7 1035.54     235 1036.24   293.7 1039.34  420.041042.179
   440.6 1044.33   479.8  1052.2  497.611054.896   509.2 1055.64   518.8 1056.92
   557.5 1064.78   596.1 1070.91  606.321072.106   692.8 1083.06   741.1 1087.76
#Mann= 10 ,-1 , 0
       0     .12       0    3.24     .06       0   24.09     .12       0
  103.98    .016       0  149.61     .12       0  213.63    .045       0
     235     .06       0  420.04     .12       0  497.61    .016       0
  606.32     .12       0
Bank Sta=213.63,235
XS Rating Curve= 0 ,0
Exp/Cntr=0.3,0.1

Type RM Length L Ch R = 1 ,2536.2  ,52.9,53,53
XS GIS Cut Line= 3
     1765788.901      241023.498     1765973.797      241083.394
     1766518.067      241110.738
#Sta/Elev= 30
       0 1093.28      68  1085.9    77.7 1084.22  100.551078.831   106.9  1077.6
   126.3 1076.78     136 1075.19  138.17 1074.43   145.8 1071.76   165.2 1062.91
   174.9 1058.73   184.6 1055.03   233.3 1037.41  239.76 1036.15     243  1035.5
  254.29 1036.43  268.29 1038.93   281.9 1040.16   320.9 1040.74   369.5 1040.03
   398.7 1040.04   418.2 1040.47   437.6 1041.47   447.4 1042.33   457.1 1043.68
   487.41049.011     535 1056.29  610.66 1068.73   680.9 1079.14   739.3  1086.2
#Mann= 8 ,-1 , 0
       0     .12       0  100.55    .016       0  138.17     .12       0
  239.76    .045       0  254.29     .06       0  268.29    .016       0
   487.4     .06       0  610.66     .12       0
Bank Sta=239.76,254.29
XS Rating Curve= 0 ,0
Exp/Cntr=0.3,0.1

Type RM Length L Ch R = 1 ,2483.2  ,91,90.6,90.4
XS GIS Cut Line= 3
     1765784.995      241075.582      1765969.89      241135.477
     1766514.161      241162.821
#Sta/Elev= 30
       0 1088.35    29.2 1084.97    38.9 1083.19   81.451073.546    87.5 1072.28
    97.2 1071.13   116.6 1070.58  123.951068.367   126.3 1067.66   145.8 1058.15
  165.76 1050.43   184.6 1043.82   194.4 1041.01   213.8 1037.77  226.361036.522
   246.2 1035.41   252.7  1035.2   261.2 1035.63   281.9 1038.39   291.7 1038.88
   369.5 1039.26   418.2 1041.04   447.4 1043.92  476.861048.766   515.5 1054.96
   573.9 1062.38   651.7 1074.16   680.9  1077.6   719.8 1081.11   739.3 1083.75
#Mann= 8 ,-1 , 0
       0     .12       0   81.45    .016       0  123.95     .12       0
  165.76    .016       0  226.36     .06       0   246.2    .045       0
   261.2     .06       0  476.86     .12       0
Bank Sta=246.2,261.2
XS Rating Curve= 0 ,0
Exp/Cntr=0.3,0.1

Type RM Length L Ch R = 1 ,2392.6  ,242.6,249.2,254.4
XS GIS Cut Line= 3
     1765794.109      241148.498     1765915.203      241224.019
     1766502.442      241247.457
#Sta/Elev= 30
       0 1071.78      19 1065.42    28.5 1062.68    38.1 1060.97   41.341060.803
    57.1 1059.35    76.1 1054.23    85.6 1051.36    95.1 1047.95   104.7 1045.43
   118.21044.175   142.7 1042.76   243.8 1034.61   250.5  1034.4   258.8 1034.42
   328.8 1035.64  386.761037.678   407.2 1038.98  431.24 1041.22   456.2 1043.77
   495.3 1048.64   524.7 1051.75   534.5 1053.65  555.76 1058.84  586.781067.491
  622.811078.078   642.3 1082.81   652.1 1084.65     701 1092.17   730.4 1095.88
#Mann= 10 ,-1 , 0
       0     .12       0   41.34    .016       0   118.2     .06       0
   243.8    .045       0   258.8     .06       0  386.76     .12       0
  431.24     .06       0  555.76     .12       0  586.78     .08       0
  622.81     .12       0
Bank Sta=243.8,258.8
XS Rating Curve= 0 ,0
Exp/Cntr=0.3,0.1

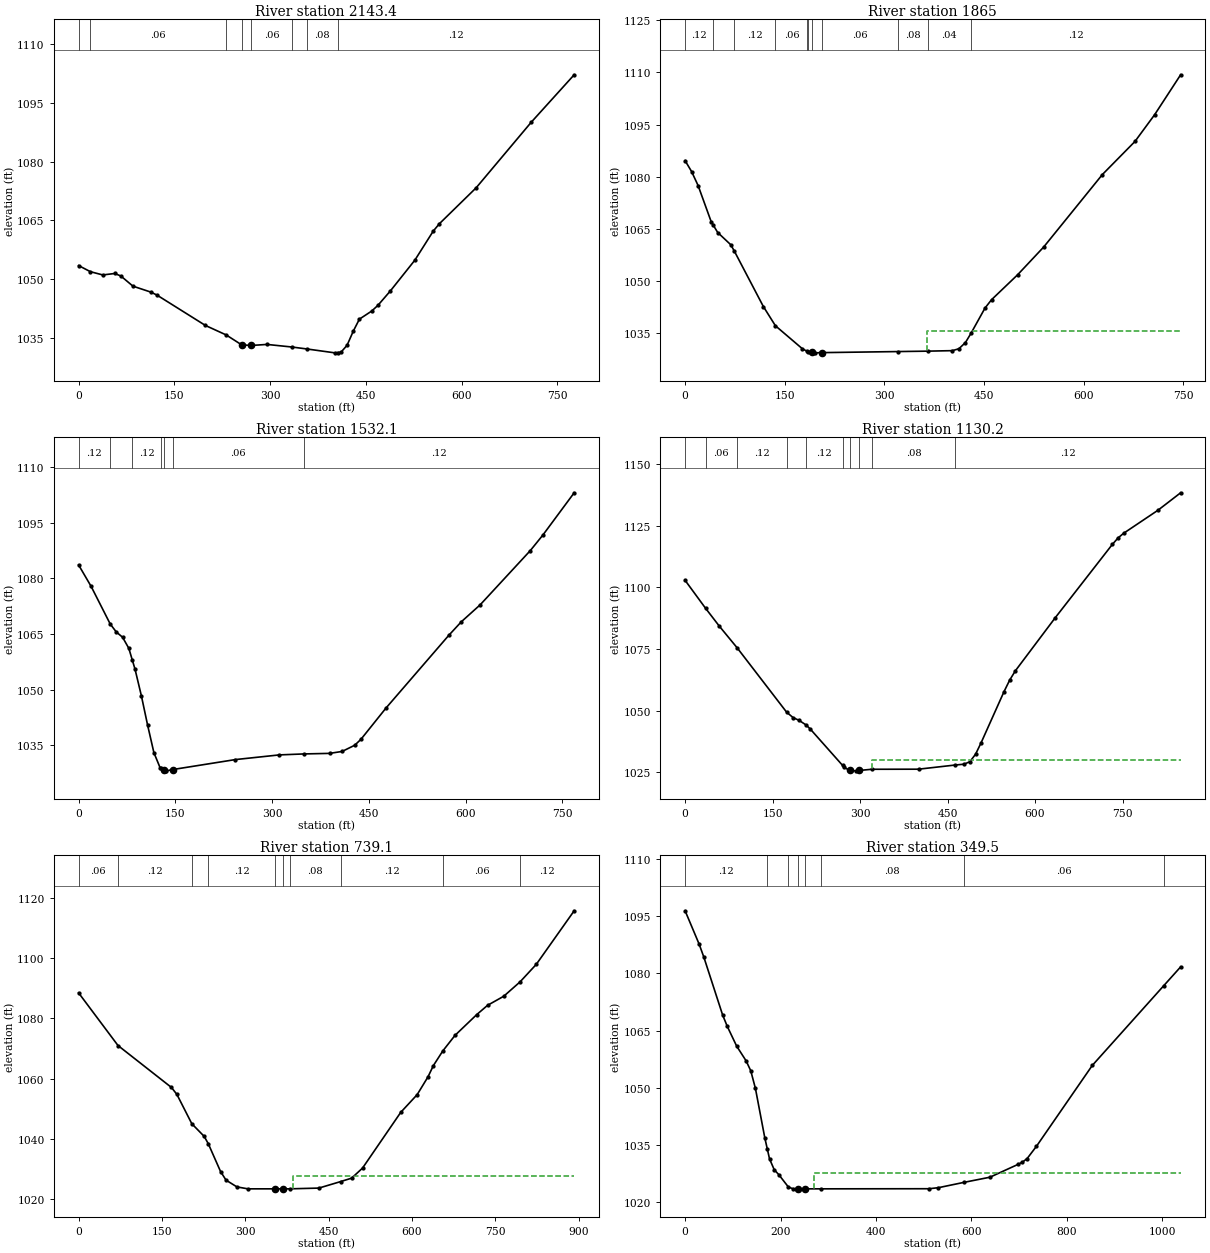
Type RM Length L Ch R = 1 ,2143.4  ,281,278.4,274.2
XS GIS Cut Line= 4
     1765768.067      241308.655     1765911.758      241445.692
      1766225.07      241543.121     1766472.495      241575.582
#Sta/Elev= 30
       0 1053.51   18.471051.956    37.8 1051.13    56.7  1051.5    66.2 1050.85
    85.1 1048.27   113.5 1046.74   122.9 1045.98   198.6 1038.27   231.21035.851
   255.4 1033.33   270.4 1033.18   295.1 1033.44  334.19 1032.78  357.031032.296
   401.2  1031.3  405.961031.374   410.9 1031.45   420.5 1033.23   430.2 1036.82
   439.8 1039.88   459.1 1041.94   468.8 1043.39   488.1 1047.02   526.7  1054.9
   555.5  1062.3   565.1 1064.17   622.6  1073.3     709 1090.01   776.2 1102.08
#Mann= 8 ,-1 , 0
       0    .016       0   18.47     .06       0   231.2     .12       0
   255.4    .045       0   270.4     .06       0  334.19     .12       0
  357.03     .08       0  405.96     .12       0
Bank Sta=255.4,270.4
XS Rating Curve= 0 ,0
Exp/Cntr=0.3,0.1

Type RM Length L Ch R = 1 ,1865    ,333.3,332.9,331.4
XS GIS Cut Line= 2
      1765682.13      241675.842     1766415.203      241813.863
#Sta/Elev= 30
       0 1084.63     9.8 1081.49    19.6 1077.46    39.3 1067.06   42.241066.133
    49.1 1063.97    68.7 1060.46   74.071058.641   117.8 1042.69  135.981037.155
   176.7 1030.52   184.2 1029.77  184.981029.692   190.7 1029.47   196.3 1029.37
   205.7 1029.43  321.041029.737  365.041029.856   402.4    1030   412.2 1030.55
     422 1032.32  430.471035.006   451.5 1042.25   461.3 1044.64   500.6 1051.82
   539.8 1059.79   628.2 1080.64   677.2 1090.14   706.7  1097.8     746 1109.32
#Mann= 11 ,-1 , 0
       0     .12       0   42.24    .016       0   74.07     .12       0
  135.98     .06       0   184.2     .12       0  184.98     .06       0
   190.7    .045       0   205.7     .06       0  321.04     .08       0
  365.04     .04       0  430.47     .12       0
#XS Ineff= 2 , 0
                          364.68          1035.6
Permanent Ineff=
       F       F
Bank Sta=190.7,205.7
XS Rating Curve= 0 ,0
Exp/Cntr=0.3,0.1

Type RM Length L Ch R = 1 ,1532.1  ,401.3,401.9,401
XS GIS Cut Line= 3
      1765634.96      241996.956     1766163.606      242078.988
     1766394.074      242042.529
#Sta/Elev= 30
       0 1083.64    19.4 1077.86   48.961067.728    58.4 1065.57    68.1 1064.16
    77.8 1061.17   83.271057.973    87.5  1055.5    97.3 1048.35     107  1040.4
   116.7 1033.02   126.4 1028.92  128.291028.755  131.71 1028.46   136.2 1028.12
   145.9 1028.47   243.2 1031.16   311.3 1032.42  349.141032.679   389.1 1032.83
   408.5 1033.35     428 1035.02   437.7 1036.62   476.6 1045.07   573.9 1064.67
   593.3 1068.32   622.5 1072.89   700.2 1087.51   719.7  1091.7   768.3 1103.12
#Mann= 7 ,-1 , 0
       0     .12       0   48.96    .016       0   83.27     .12       0
  128.29     .06       0  131.71    .045       0   145.9     .06       0
  349.14     .12       0
Bank Sta=131.71,145.9
XS Rating Curve= 0 ,0
Exp/Cntr=0.3,0.1

Type RM Length L Ch R = 1 ,1130.2  ,388.5,391.1,392.8
XS GIS Cut Line= 3
     1765485.608      242344.269     1765673.015      242398.498
     1766321.179      242489.678
#Sta/Elev= 30
       0 1102.83      35 1091.53    58.5 1084.31   89.111075.509  174.081049.381
   185.3 1047.16   195.1 1046.12  207.36 1044.21   214.6 1042.56  270.051027.798
   273.2 1026.97  281.93  1025.8   292.8 1025.61  298.07 1025.75  320.171026.244
   400.2 1026.28  463.391027.973   478.4 1028.31   488.2 1029.32     498 1032.34
   507.7 1037.09   546.8 1057.72   556.6 1062.43   566.3 1066.18   634.7  1087.7
   732.4 1117.36   742.2 1119.99     752 1121.93   810.6 1131.22   849.6 1138.32
#Mann= 10 ,-1 , 0
       0     .12       0      35     .06       0   89.11     .12       0
  174.08    .016       0  207.36     .12       0  270.05     .06       0
  281.93    .045       0  298.07     .06       0  320.17     .08       0
  463.39     .12       0
#XS Ineff= 2 , 0
                           320.7         1029.89
Permanent Ineff=
       F       F
Bank Sta=281.93,298.07
XS Rating Curve= 0 ,0
Exp/Cntr=0.3,0.1

Type RM Length L Ch R = 1 ,739.1   ,385.1,389.7,393.7
XS GIS Cut Line= 3
     1765422.545      242667.523     1766024.108      242813.356
     1766279.316      242717.002
#Sta/Elev= 30
       0 1088.47   70.851071.021     167 1057.12   176.8 1054.82  203.711045.077
     226 1040.88  233.371038.436   255.4 1029.24   265.3 1026.37   284.9 1024.13
   304.6 1023.49   353.1 1023.49   368.1 1023.49  379.99 1023.49   432.3 1023.74
  471.641025.902   491.3 1027.04   510.9 1030.37   579.7 1048.86   609.2 1054.72
   628.7 1060.62   638.5 1064.39  655.461069.246   677.4  1074.4   716.4 1081.27
   735.9 1084.35   765.1 1087.37  794.431092.136   823.6 1097.94   891.8 1115.71
#Mann= 10 ,-1 , 0
       0     .06       0   70.85     .12       0  203.71    .016       0
  233.37     .12       0   353.1    .045       0   368.1     .12       0
  379.99     .08       0  471.64     .12       0  655.46     .06       0
  794.43     .12       0
#XS Ineff= 2 , 0
                             386         1027.66
Permanent Ineff=
       F       F
Bank Sta=353.1,368.1
XS Rating Curve= 0 ,0
Exp/Cntr=0.3,0.1

Type RM Length L Ch R = 1 ,349.5   ,301.8,297,291
XS GIS Cut Line= 3
     1765302.753      242914.919     1765886.087      243175.336
     1766248.066      243006.065
#Sta/Elev= 30
       0  1096.4    29.5 1087.63    39.3 1084.24    78.6 1069.09    88.4 1066.08
   108.1  1060.9   127.8 1057.06   137.6 1054.45   147.4  1049.8   167.1 1036.81
   172.41033.863   176.9 1031.36   186.7 1028.52   196.6 1027.17  216.581023.943
     226 1023.52   235.9 1023.49   250.9 1023.49  284.19 1023.49   511.1 1023.52
   530.7 1023.79  583.711025.171   638.8 1026.54   697.3 1029.88     707  1030.5
   716.8 1031.44   736.3 1034.65   853.2 1055.84 1002.96 1076.75  1038.4 1081.69
#Mann= 8 ,-1 , 0
       0     .12       0   172.4    .016       0  216.58     .12       0
   235.9    .045       0   250.9     .06       0  284.19     .08       0
  583.71     .06       0 1002.96     .12       0
#XS Ineff= 2 , 0
                          269.82         1027.77
Permanent Ineff=
       F       F
Bank Sta=235.9,250.9
XS Rating Curve= 0 ,0
Exp/Cntr=0.3,0.1

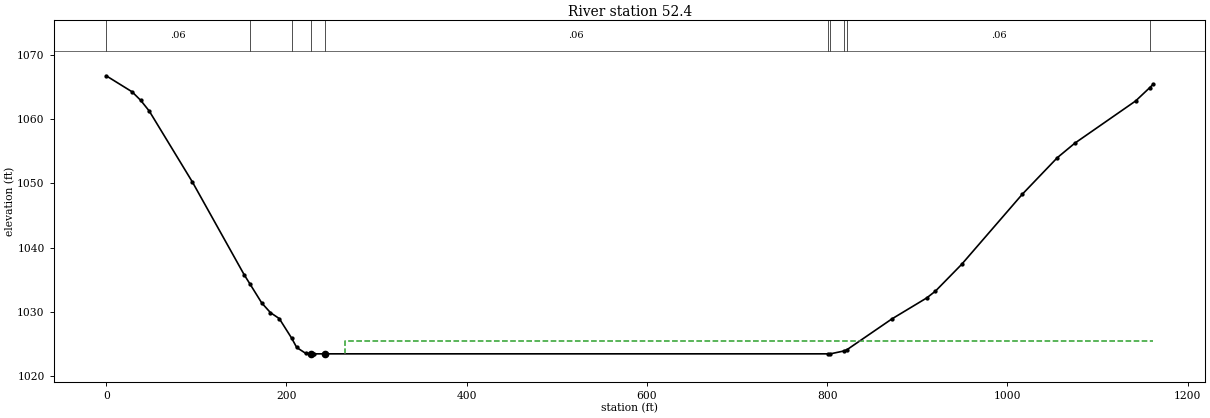
Type RM Length L Ch R = 1 ,52.4    ,53.1,52.4,52.1
XS GIS Cut Line= 4
     1765190.774      243154.502     1765305.358      243256.065
     1765888.691      243362.836     1766203.795      243092.002
#Sta/Elev= 30
       0 1066.73    28.7 1064.24    38.3 1062.91    47.8 1061.24    95.7  1050.2
   153.1 1035.79  159.771034.298   172.6  1031.4   182.3 1029.89     192 1028.98
  205.791025.926   211.4 1024.48   221.2 1023.58   227.4 1023.52   230.9 1023.49
   242.4 1023.49  800.74 1023.49  803.61 1023.49  818.461023.932  822.041024.141
   871.8 1028.92   910.4 1032.18   920.1 1033.24   949.1 1037.39  1016.7 1048.34
  1055.4    1054  1074.7 1056.24  1142.3 1062.82 1157.881064.881  1161.6  1065.4
#Mann= 10 ,-1 , 0
       0     .06       0  159.77    .016       0  205.79     .12       0
   227.4    .045       0   242.4     .06       0  800.74     .08       0
  803.61     .06       0  818.46     .08       0  822.04     .06       0
 1157.88     .12       0
#XS Ineff= 2 , 0
                          264.89          1025.5
Permanent Ineff=
       F       F
Bank Sta=227.4,242.4
XS Rating Curve= 0 ,0
Exp/Cntr=0.3,0.1

Chan Stop Cuts=-1
Use User Specified Reach Order=0
Composite Channel Slope=5